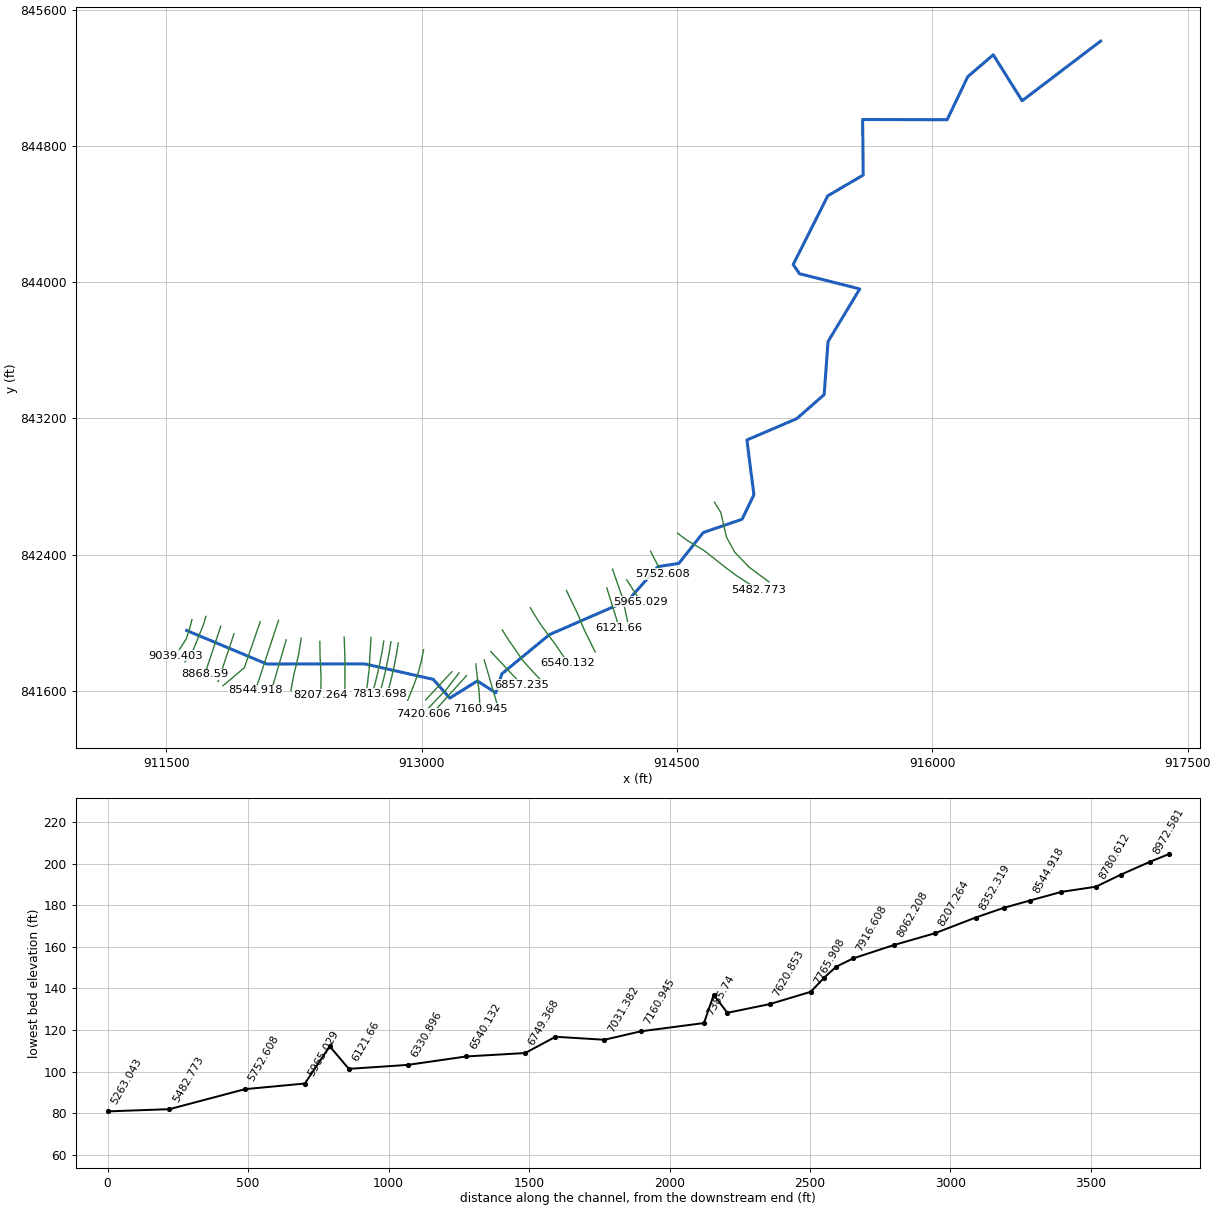
--- 16792_ras.prj (project) ---

Proj Title=16792
Current Plan=p01
Default Exp/Contr=0.3,0.1
English Units
Geom File=g01
Flow File=f01
Plan File=p01
Y Axis Title=Elevation
X Axis Title(PF)=Main Channel Distance
X Axis Title(XS)=Station
BEGIN DESCRIPTION:
RFD model 16792 exported to HEC-RAS
END DESCRIPTION:

--- 16792_ras.p01 (plan) ---

Plan Title=Plan 01
Program Version=4.10
Short Identifier=Plan 01
Geom File=g01
Flow File=f01
Subcritical Flow
Calc Critical at every XS
Secant Critical Depth

--- 16792_ras.f01 (steady flow) ---

Flow Title=Flow 01
Program Version=5.01
Number of Profiles= 6
Profile Names=10yr,25yr,50yr,100yr,100plus,500yr
River Rch & RM=16792,36,9039.403
  159.82   250.4  333.41  407.23  594.55 1019.81
River Rch & RM=16792,36,7468.675
  161.59   253.2  337.16  411.83  601.28 1029.82
River Rch & RM=16792,36,7420.606
  164.23  257.39  342.77  418.72  611.34 1044.76
River Rch & RM=16792,36,7160.945
  167.31  262.25   349.3  426.74  623.03 1062.09
River Rch & RM=16792,36,6857.235
  170.28     267  355.69  434.62  634.55 1079.31
River Rch & RM=16792,36,6749.368
  195.37  307.35  410.41  502.44  733.56 1227.47
River Rch & RM=16792,36,6540.132
  205.17  323.18  431.91  529.13  772.53 1285.23
River Rch & RM=16792,36,6330.896
  210.18  331.29  442.95  542.86  792.58 1314.87
River Rch & RM=16792,36, 6121.66
  221.19  349.31  467.66  573.77  837.71 1382.28
River Rch & RM=16792,36,5965.029
  225.15  355.81  476.59  584.97  854.06 1406.67
Boundary for River Rch & Prof#=16792,36,1
Up Type= 0
Dn Type= 2
Boundary for River Rch & Prof#=16792,36,2
Up Type= 0
Dn Type= 2
Boundary for River Rch & Prof#=16792,36,2
Up Type= 0
Dn Type= 2
Boundary for River Rch & Prof#=16792,36,2
Up Type= 0
Dn Type= 2
Boundary for River Rch & Prof#=16792,36,2
Up Type= 0
Dn Type= 2
Boundary for River Rch & Prof#=16792,36,2
Up Type= 0
Dn Type= 2

--- 16792_ras.g01 (geometry) ---

Geom Title=16792
Program Version=4.10

River Reach=16792,36
Reach XY= 30
911620.648231804841953.870626168912090.918464361841757.178001756
912667.060109494841757.564128619 913068.96473525841666.849100841
913165.820429488841556.879434703913327.317305041841657.577408577
913435.635330683841588.212469899 913471.63900074841699.632634889
913751.030191508841929.622058125914213.336670853842131.000578382
914388.527987803842328.993534759914510.967618526842347.783162489
 914653.98141876842528.998519323914882.644639825842607.339059541
914951.554192685 842750.88120668914910.622124405843072.548988314
915203.581500877843198.051100729915364.120355649843338.918021055
915387.043751416843651.132860418915573.395685185843959.650369937
915219.264587784844048.999133499915182.403949684844103.092585325
915385.477855186844506.413363468915593.559152451844628.233178411
915590.055358837844954.681303984916086.095344384844953.039715442
 916207.54472825845206.065018256916357.219822828845334.492843619
916526.830536613845064.628776066916987.778868321845415.050500871

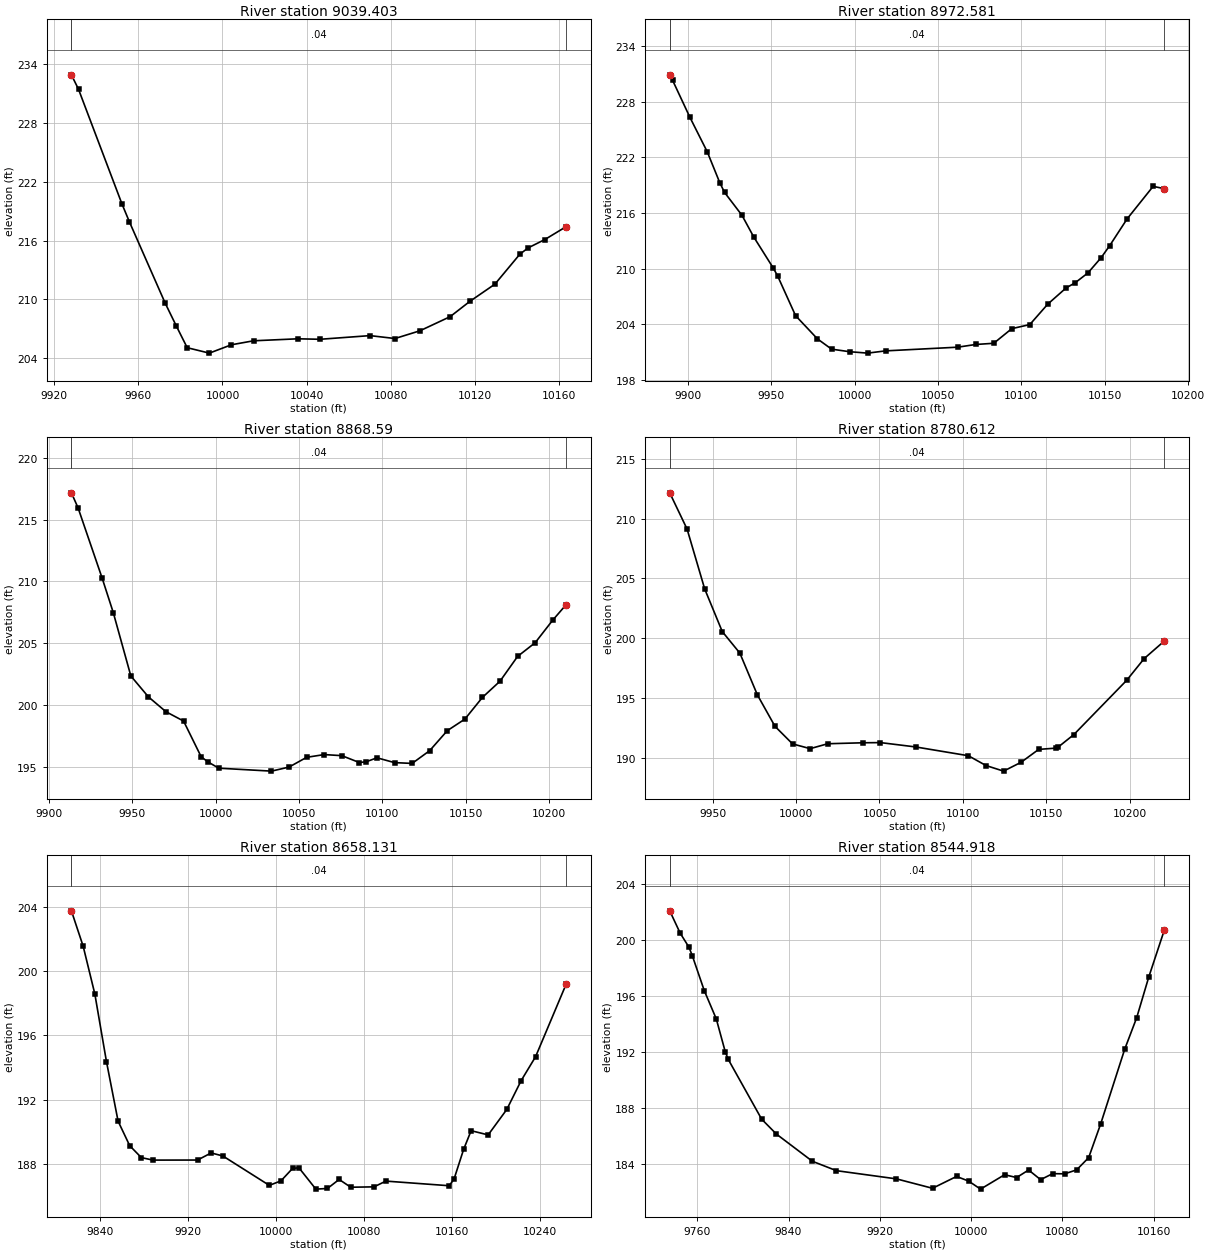
Type RM Length L Ch R = 1 ,9039.403,66.821900,66.821900,66.821900
XS GIS Cut Line= 4
911651.709600688842018.272442483911639.540924421841969.887843232
911618.371829624841905.082018635911555.303003728841806.518345898
#Sta/Elev= 22
9928.201232.90539931.575231.43549952.198219.7571 9955.71217.94379972.821209.6016
9978.092 207.2859983.234205.08249993.754204.529510004.27205.383210014.79205.7875
10035.83205.990310046.37205.941510070.11206.314610081.98 206.01910093.85 206.809
10108.18208.2462 10117.6209.813510129.47211.563210141.34214.622910145.29215.2647
10153.21216.113310163.28217.4195
#Mann= 3 , 0 , 0
9928.201    0.04       09928.201    0.04       010163.28    0.04       0
#XS Ineff= 2 , 0
       0                10068.49       0
Bank Sta=9928.201,10163.28
Exp/Cntr=0.3,0.1

Type RM Length L Ch R = 1 ,8972.581,103.990700,103.990700,103.990700
XS GIS Cut Line= 4
911733.233751525842036.623944659911719.416722151841988.232709418
911649.226882424841815.907914643911610.673487229841769.874774315
#Sta/Elev= 30
9889.238230.92939890.927230.35019901.327226.33999911.726222.61339919.228219.2759
9922.126218.21459932.526215.75359939.563213.41529951.272210.05649953.852209.2153
9964.649204.90779977.782202.39359986.245201.28579997.043201.009910007.84200.8569
10018.64201.100810061.83201.499610072.63201.791810083.42201.921210094.22203.5014
10105.02203.942210115.82206.157610126.82207.908410132.22208.459510139.86 209.524
10147.79211.176710152.91 212.47410163.37215.372410178.94218.879410185.68218.6242
#Mann= 3 , 0 , 0
9889.238    0.04       09889.238    0.04       010185.68    0.04       0
#XS Ineff= 2 , 0
       0                10074.96       0
Bank Sta=9889.238,10185.68
Exp/Cntr=0.3,0.1

Type RM Length L Ch R = 1 , 8868.59,87.977900,87.977900,87.977900
XS GIS Cut Line= 2
911820.834051344841978.809955052911727.180841228841697.430170328
#Sta/Elev= 30
9913.537217.17489917.553215.95159932.011210.25219938.632207.48419949.171202.3503
 9959.71200.6558 9970.25199.45279980.789198.69889991.328195.80879995.342195.3966
10001.87194.884210033.49194.645710044.03194.974610054.56195.7637 10065.1195.9853
10075.64195.898410086.18195.339910090.34195.406310096.72195.725210107.26195.3337
 10117.8195.270410128.34196.304510138.88197.920510149.42 198.85610159.96 200.616
 10170.5201.927610181.04203.932910191.58205.043710202.12206.871710210.09208.1148
#Mann= 3 , 0 , 0
9913.537    0.04       09913.537    0.04       010210.09    0.04       0
#XS Ineff= 2 , 0
       0                10065.26       0
Bank Sta=9913.537,10210.09
Exp/Cntr=0.3,0.1

Type RM Length L Ch R = 1 ,8780.612,122.481500,122.481500,122.481500
XS GIS Cut Line= 2
 911898.48790107841934.883209275911804.834969008841653.503116665
#Sta/Elev= 24
9924.255 212.1479934.672209.11569945.211204.1226 9955.75200.5591 9966.29198.7612
9976.829195.26389987.368 192.6419997.908191.173710008.45190.779110018.99191.1886
10040.07 191.269 10050.6 191.28410071.68190.9218 10103.3190.187310113.84189.3702
10124.38188.901410134.92189.641910145.46 190.718   10156190.824110156.96190.8901
10166.54191.955510198.16196.481110208.69198.301810220.81199.7737
#Mann= 3 , 0 , 0
9924.255    0.04       09924.255    0.04       010220.81    0.04       0
#XS Ineff= 2 , 0
       0                10036.31       0
Bank Sta=9924.255,10220.81
Exp/Cntr=0.3,0.1

Type RM Length L Ch R = 1 ,8658.131,113.212900,113.212900,113.212900
XS GIS Cut Line= 3
912052.334574512 842005.13909359911959.500688602841735.470844918
 911833.82164935841629.281184175
#Sta/Elev= 30
9813.755203.73629824.478201.52849835.054198.5675 9845.63194.36119856.206190.6546
9866.782189.12959877.358188.38889887.934188.23419928.453188.23799940.814188.6799
 9951.39188.49379993.694186.663610004.27186.942310014.85187.718510020.62187.7553
   10036186.429310046.57186.470310057.15187.031210067.73186.547410088.88186.5709
10099.68186.928210157.21186.640810161.66187.058710170.31188.895410177.16190.0636
10192.65189.801610209.58191.382910222.67193.180410235.76194.663510263.49 199.166
#Mann= 3 , 0 , 0
9813.755    0.04       09813.755    0.04       010263.49    0.04       0
#XS Ineff= 2 , 0
       09972.216        10024.97       0
Bank Sta=9813.755,10263.49
Exp/Cntr=0.3,0.1

Type RM Length L Ch R = 1 ,8544.918,92.627200,92.627200,92.627200
XS GIS Cut Line= 2
912160.272949143842013.766615921912024.287042743841601.954784901
#Sta/Elev= 30
 9735.83202.05659745.062200.45599752.646199.47029755.593 198.8689766.125196.3696
9776.656194.35189784.538192.00369787.187191.4607 9816.43187.20769829.311186.1481
9860.904 184.2069881.967183.53739934.622182.95179966.215182.28149987.278183.1253
9997.809182.797910008.34182.2214 10029.4183.247110039.93183.046810050.46183.5841
   10061182.895410071.53183.324810082.06183.311810092.59183.594210103.12184.4664
10113.65186.870610134.71192.192410145.24194.443710155.78197.331710169.51200.6988
#Mann= 3 , 0 , 0
 9735.83    0.04       0 9735.83    0.04       010169.51    0.04       0
#XS Ineff= 2 , 0
       09968.021         10044.9       0
Bank Sta=9735.83,10169.51
Exp/Cntr=0.3,0.1

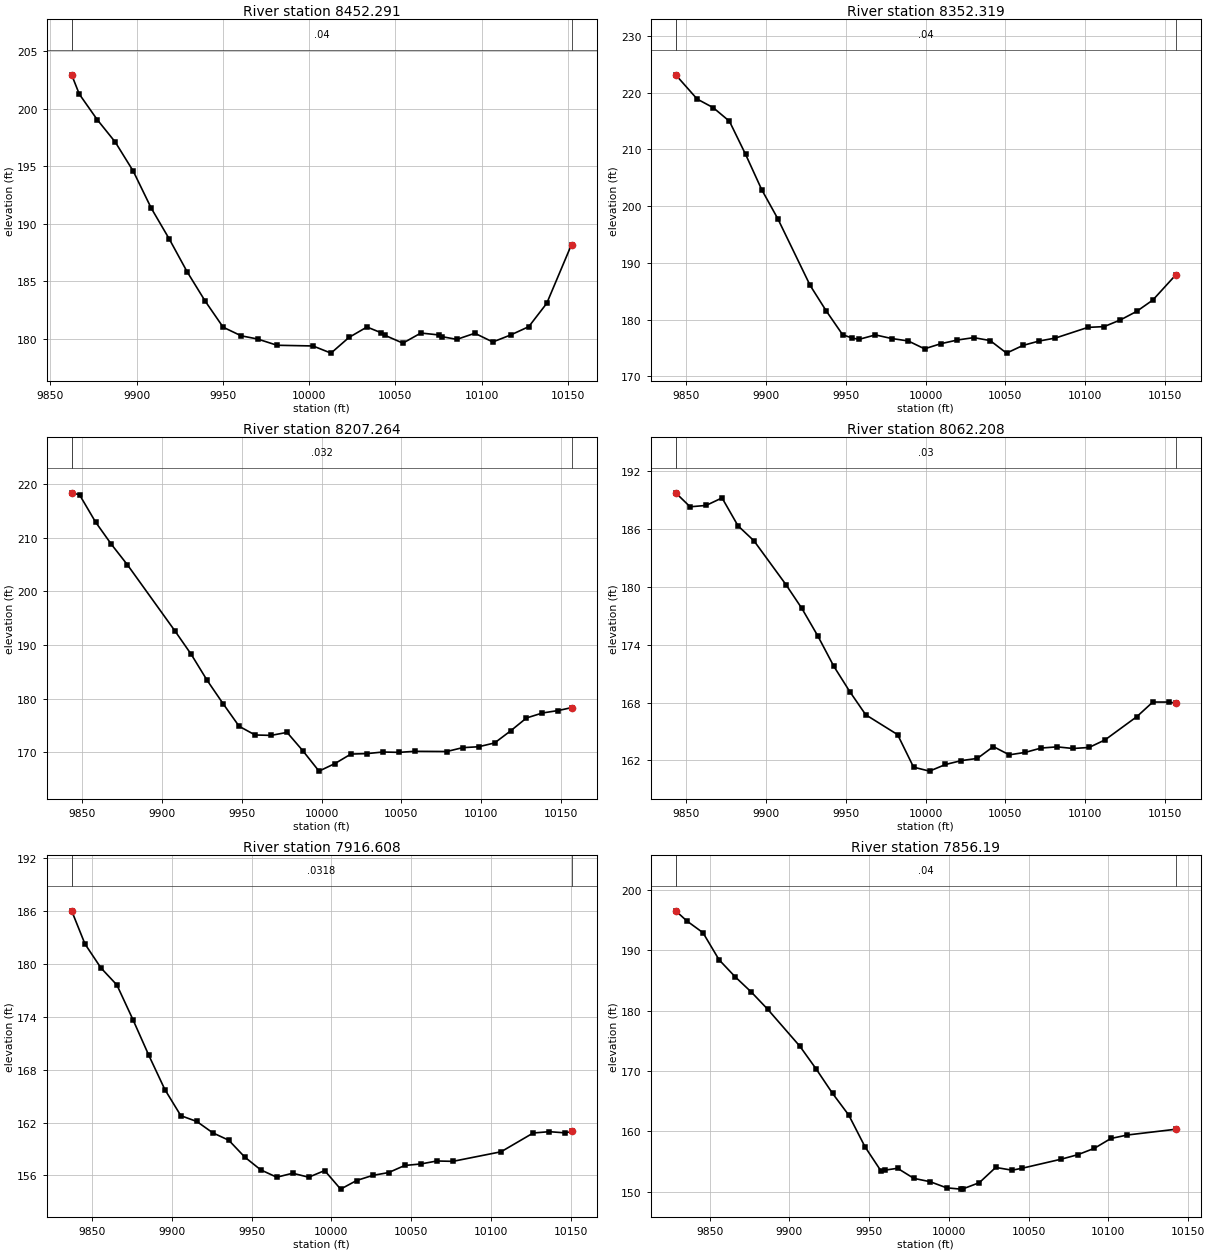
Type RM Length L Ch R = 1 ,8452.291,99.971700,99.971700,99.971700
XS GIS Cut Line= 2
912205.242679567841899.253105951912123.941055532841621.199190309
#Sta/Elev= 30
9862.408202.95989866.839201.27799877.257199.04979887.676197.10379898.095194.5743
9908.514191.35499918.932188.67669929.351185.8049 9939.77183.26259950.188180.9866
9960.607180.23849970.169179.95719981.445179.413210002.28179.3522 10012.7178.7286
10023.12180.094810033.54181.002910041.43180.522810043.96180.278510054.38179.5989
10064.79 180.47810075.21180.312210077.07180.160710085.63 179.92610096.05180.4586
10106.47179.698510116.89180.313310127.31181.031210137.73183.0639 10152.1188.1854
#Mann= 3 , 0 , 0
9862.408    0.04       09862.408    0.04       0 10152.1    0.04       0
#XS Ineff= 2 , 0
       09964.517        10049.45       0
Bank Sta=9862.408,10152.1
Exp/Cntr=0.3,0.1

Type RM Length L Ch R = 1 ,8352.319,145.055300,145.055300,145.055300
XS GIS Cut Line= 6
912293.145336173841908.260494416912278.268946353841813.081620873
912264.829844926841755.300096437912264.320104638841753.366145858
912250.504436936841695.684059784912232.715320044841600.976060459
#Sta/Elev= 30
9843.342223.17399856.763218.90459866.885 217.3739877.006214.98829887.127209.1504
9897.249202.9136 9907.37197.76769927.613186.01479937.735181.49929947.974177.3175
9954.106176.7153 9958.24176.49899968.507177.28069978.774176.64089989.041176.2212
 9999.31174.8292 10009.6175.733410019.89176.380410030.17176.801510040.45 176.285
10050.73174.067310061.01175.426310071.18176.204710081.36176.727810101.71178.6089
10111.88178.747310122.06  179.9210132.23181.424610142.41183.430710156.68 187.834
#Mann= 3 , 0 , 0
9843.342    0.04       09843.342    0.04       010156.68    0.04       0
#XS Ineff= 2 , 0
       09968.516        10031.07       0
Bank Sta=9843.342,10156.68
Exp/Cntr=0.3,0.1

Type RM Length L Ch R = 1 ,8207.264,145.055400,145.055400,145.055400
XS GIS Cut Line= 6
 912402.70566819841889.945127243912403.851868623 841806.06168236
912407.503920966841734.362992224912407.600065614841732.365304509
912409.967463473841673.083806709 912407.76482356841576.772162264
#Sta/Elev= 30
9843.317218.32379848.263217.95589858.264212.90039868.265208.71919878.265204.9291
9908.268192.52599918.269188.24719928.271 183.3989938.284179.04989948.297174.8582
 9958.31 173.2399968.323173.16439978.336173.72079988.349170.26279998.362166.5096
10008.37167.922310018.38169.687110028.39169.7721 10038.4170.0683 10048.4170.0038
10058.41170.197510078.42170.159310088.42170.880510098.42171.046810108.43171.7547
10118.43173.992110128.43176.406410138.43177.334710148.44 177.79710156.67178.3303
#Mann= 3 , 0 , 0
9843.317   0.032       09843.317   0.032       010156.67   0.032       0
#XS Ineff= 2 , 0
       0                10049.51       0
Bank Sta=9843.317,10156.67
Exp/Cntr=0.3,0.1

Type RM Length L Ch R = 1 ,8062.208,145.600300,145.600300,145.600300
XS GIS Cut Line= 5
912545.588463059841914.026951271912550.104756615841791.915333965
912550.195419408 841758.42339434912550.239450073841756.423879073
912549.874474794841600.746634118
#Sta/Elev= 30
9843.313189.74979852.346188.30179862.353188.4424 9872.36 189.2239882.366186.3317
9892.373184.77559912.387180.23969922.394177.76759932.401174.91039942.407 171.773
9952.414169.14659962.421166.74089982.423164.67929992.423161.305910002.42160.8953
10012.42161.582610022.42161.987210032.42162.213410042.42  163.4410052.42162.5849
10062.42162.838110072.42163.289210082.42163.410110092.42163.242710102.42163.3485
10112.42164.129610132.42166.547610142.42168.058910152.42168.054910156.68167.9566
#Mann= 3 , 0 , 0
9843.313    0.03       09843.313    0.03       010156.68    0.03       0
#XS Ineff= 2 , 0
       0                   10043       0
Bank Sta=9843.313,10156.68
Exp/Cntr=0.3,0.1

Type RM Length L Ch R = 1 ,7916.608,60.418300,60.418300,60.418300
XS GIS Cut Line= 5
912703.088910659841913.320840431912693.875510024841757.910103461
912693.825624836841755.910725691912692.302919453841728.276757231
912677.598544217841601.127189677
#Sta/Elev= 30
9837.149186.04889845.485182.28939855.502 179.565 9865.52 177.6259875.538173.7044
9885.555 169.6239895.573165.7559 9905.59162.78449915.608162.12659925.625160.8367
9935.643 159.997 9945.66158.08349955.678156.63199965.696155.79889975.713156.2492
9985.731155.79649995.745156.551710005.76154.444310015.78155.422710025.81156.0006
10035.87156.326710045.94157.130910056.01157.301510066.07157.639510076.14157.5991
10106.34158.686910126.47160.817110136.54160.968110146.61160.832210150.51160.9933
#Mann= 3 , 0 , 0
9837.149  0.0318       09837.149  0.0318       010150.51  0.0318       0
#XS Ineff= 2 , 0
       09978.154                       0
Bank Sta=9837.149,10150.51
Exp/Cntr=0.3,0.1

Type RM Length L Ch R = 1 , 7856.19,42.491600,42.491600,42.491600
XS GIS Cut Line= 6
912778.035008726841891.877959266912767.226619254841823.918575735
912751.150063259841743.160648047912749.760113268841736.784471169
912736.263273868841679.007223142912712.036629719841585.747337698
#Sta/Elev= 30
9828.725196.54589835.689 194.8749845.815192.9217 9855.94188.42189866.066185.5986
9876.192 183.0689886.317180.25889906.632174.08839916.828170.31949927.024166.3065
 9937.22162.69619947.417157.43839957.613153.36559960.162153.59089967.809153.8889
9978.005152.21749988.239151.66599998.508150.654510007.33150.436510008.78150.4808
10019.05151.504510029.32154.029710039.59153.574310045.74153.888210070.54 155.407
10080.88156.148310091.21157.204810101.54158.828510111.87159.404710142.09160.3539
#Mann= 3 , 0 , 0
9828.725    0.04       09828.725    0.04       010142.09    0.04       0
#XS Ineff= 2 , 0
       0 9961.85                       0
Bank Sta=9828.725,10142.09
Exp/Cntr=0.3,0.1

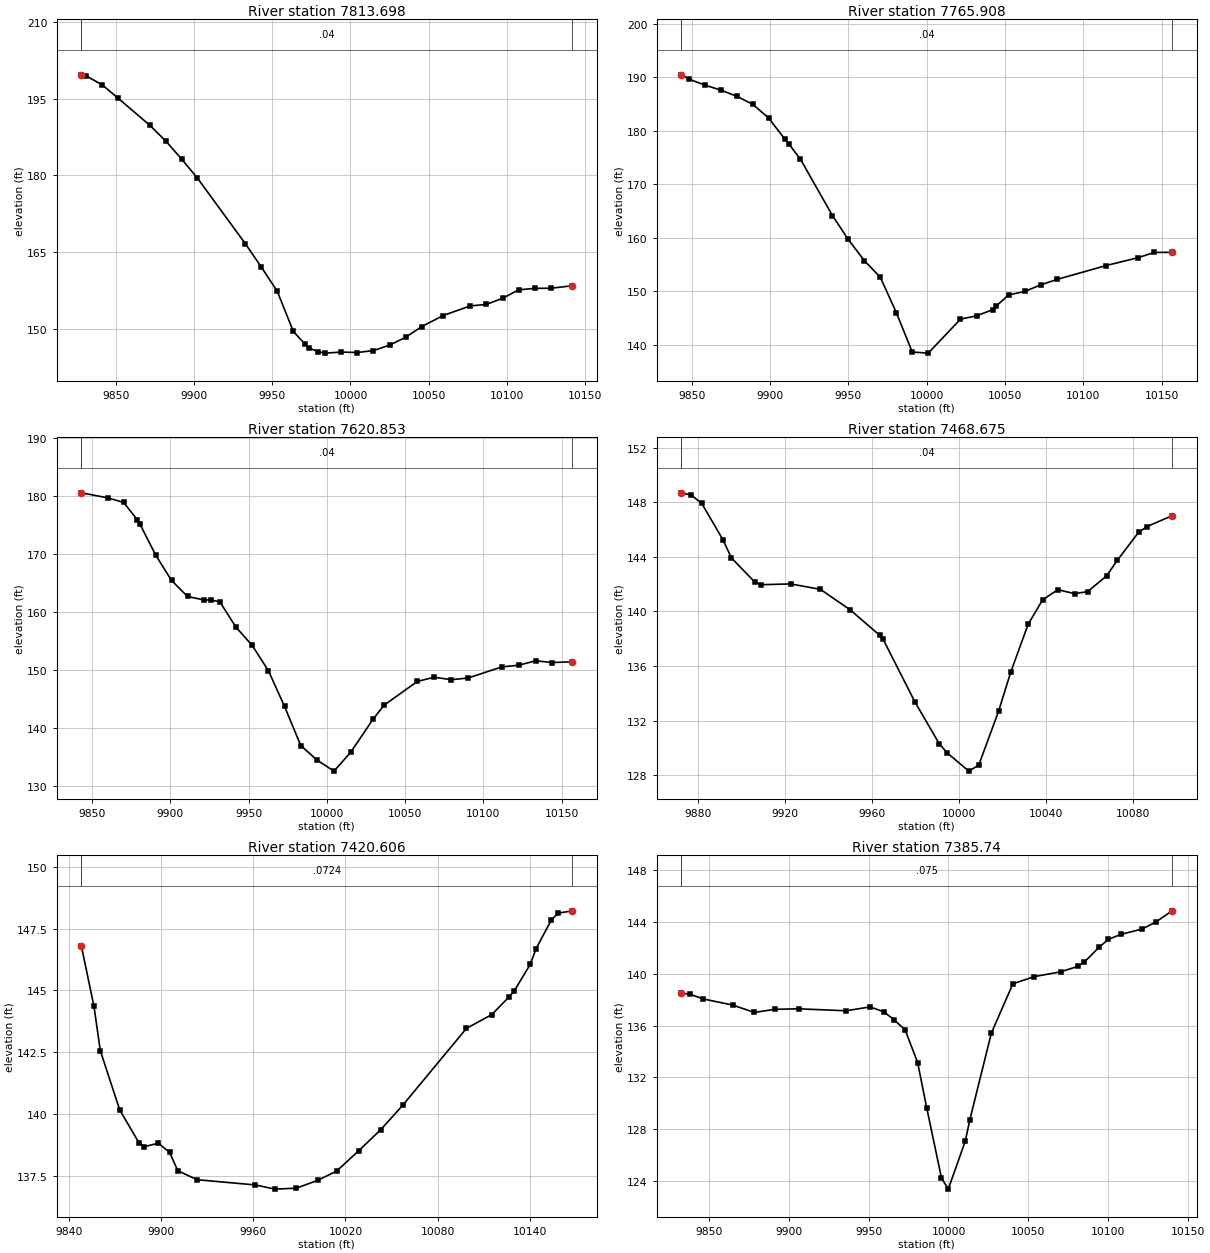
Type RM Length L Ch R = 1 ,7813.698,47.790200,47.790200,47.790200
XS GIS Cut Line= 6
912820.250485106841888.116170871912809.442140127841820.156776022
912793.365636804841739.398832701912791.975690964841733.022654504
 912778.47888912841675.245393962912754.252305446841581.985486726
#Sta/Elev= 30
9828.216199.64869831.371199.42679841.497197.67829851.623195.07999871.874 189.781
    9882186.72589892.125183.20199902.287179.44749932.876166.62499943.072162.0526
9953.269157.31499963.465149.49379971.001146.96879973.661146.18079979.372145.5231
9983.873145.22869994.137145.435510004.41145.348910014.68145.732710024.94146.7846
10035.21148.327810045.48150.414610059.07152.565110076.48154.464710086.81154.7515
10097.14155.964610107.48157.610510117.81 157.89210128.14157.922410141.59158.4026
#Mann= 3 , 0 , 0
9828.216    0.04       09828.216    0.04       010141.59    0.04       0
#XS Ineff= 2 , 0
       0                               0
Bank Sta=9828.216,10141.59
Exp/Cntr=0.3,0.1

Type RM Length L Ch R = 1 ,7765.908,145.055300,145.055300,145.055300
XS GIS Cut Line= 6
912863.142555941841880.097046817912852.334255431841812.137636031
912836.257804542841731.379671538912834.867862831  841725.0034916
912821.371098239841667.226214618912797.144574384841573.966279116
#Sta/Elev= 29
9843.318190.43819848.479189.59669858.605188.4962 9868.73187.55929878.856 186.406
9888.982184.92219899.107 182.3419909.233178.48749912.131177.45719919.409174.6401
9939.802164.13369949.697159.74169960.194155.6886 9970.39152.58039980.586145.9963
9990.783138.6039   10001138.401110021.54144.745210031.81145.378310042.08146.5148
10044.38   147.210052.35149.284710062.63149.936410072.96151.1825 10083.3152.1872
10114.29154.757310134.96156.246210145.29157.227610156.69157.2527
#Mann= 3 , 0 , 0
9843.318    0.04       09843.318    0.04       010156.69    0.04       0
#XS Ineff= 2 , 0
       0                               0
Bank Sta=9843.318,10156.69
Exp/Cntr=0.3,0.1

Type RM Length L Ch R = 1 ,7620.853,152.177400,152.177400,152.177400
XS GIS Cut Line= 6
913011.988571553841841.425164753912998.453317577841773.795691229
 912981.08728716841706.492874036912975.504087193841690.239874929
912952.297405677841627.102945827912918.292339447 841543.31986568
#Sta/Elev= 30
9843.337180.52899860.088179.66499870.286178.86299878.948175.90569880.484175.2331
9890.683169.81499900.881 165.4029911.079 162.6439921.391162.05549926.129162.0368
9931.719161.70629942.046157.33779952.374154.19279962.701149.84699973.029143.6627
9983.393136.91589993.967134.375410004.59132.510610015.24135.758810029.43141.4352
10036.55 143.88510057.85 147.99110068.54148.714710079.33148.290910090.12148.5679
10111.71  150.49 10122.5150.783810133.29151.541810144.08151.251910156.69151.3736
#Mann= 3 , 0 , 0
9843.337    0.04       09843.337    0.04       010156.69    0.04       0
#XS Ineff= 2 , 0
       0                               0
Bank Sta=9843.337,10156.69
Exp/Cntr=0.3,0.1

Type RM Length L Ch R = 1 ,7468.675,48.069400,48.069400,48.069400
XS GIS Cut Line= 2
913177.996215457841711.826265441913024.534461599841546.535491245
#Sta/Elev= 29
9872.329148.68169876.733148.53019881.644147.9238 9891.43145.24979895.289143.9243
9906.127142.13789908.935141.9519 9922.58142.00629936.226 141.6129949.871140.1172
9963.517138.24199964.916138.00199979.614 133.3819990.808 130.3159994.311129.6552
10004.45128.291510009.01128.7264 10018.1132.660610023.71135.542610031.74139.0536
 10038.4140.846310045.39141.5837 10053.1141.294810059.03141.4424 10067.8142.5986
10072.68143.735510082.49145.789710086.33146.209110097.88147.0024
#Mann= 3 , 0 , 0
9872.329    0.04       09872.329    0.04       010097.88    0.04       0
#XS Ineff= 2 , 0
       0                               0
Bank Sta=9872.329,10097.88
Exp/Cntr=0.3,0.1

Type RM Length L Ch R = 1 ,7420.606,34.866000,34.866000,34.866000
XS GIS Cut Line= 3
  913219.9726771841704.748189066913145.919617877841608.355219028
913008.745616433841465.251765133
#Sta/Elev= 27
9847.984146.77839856.147144.35289860.277 142.5659872.887140.17659885.498138.8349
9888.976138.68649898.108138.8231 9905.39138.45819910.718137.71499923.329137.3494
9961.159137.13849974.186136.96899988.039137.007510001.89137.322210014.22137.6965
10028.67138.521110043.12139.3787 10057.3140.356910098.86143.466510115.38144.0256
10126.56144.736310129.83144.964410140.41146.054410144.28 146.69510154.27 147.861
10158.73148.125110167.77148.2187
#Mann= 3 , 0 , 0
9847.984  0.0724       09847.984  0.0724       010167.77  0.0724       0
#XS Ineff= 2 , 0
       0                               0
Bank Sta=9847.984,10167.77
Exp/Cntr=0.3,0.1

Type RM Length L Ch R = 1 , 7385.74,224.794500,224.794500,224.794500
XS GIS Cut Line= 2
913264.173897326841688.883383175913058.214405978841461.116583584
#Sta/Elev= 30
9832.845138.4883 9838.08 138.4259846.523138.05349865.045137.57959878.527 137.013
9891.252137.25169906.161137.2927 9935.98137.1401 9950.89137.4396 9959.42 137.073
  9965.8136.46639972.902135.66139980.709133.14149986.384129.64899995.619124.2384
9999.866123.376210010.53127.085610013.35128.723510026.83135.410710040.31139.2245
10053.79139.780410070.17140.146810080.76140.560310085.08140.906410094.24142.0445
10099.99 142.64610107.72143.029310121.21143.451510129.81143.993310139.92144.8542
#Mann= 3 , 0 , 0
9832.845   0.075       09832.845   0.075       010139.92   0.075       0
#XS Ineff= 2 , 0
       0                               0
Bank Sta=9832.845,10139.92
Exp/Cntr=0.3,0.1

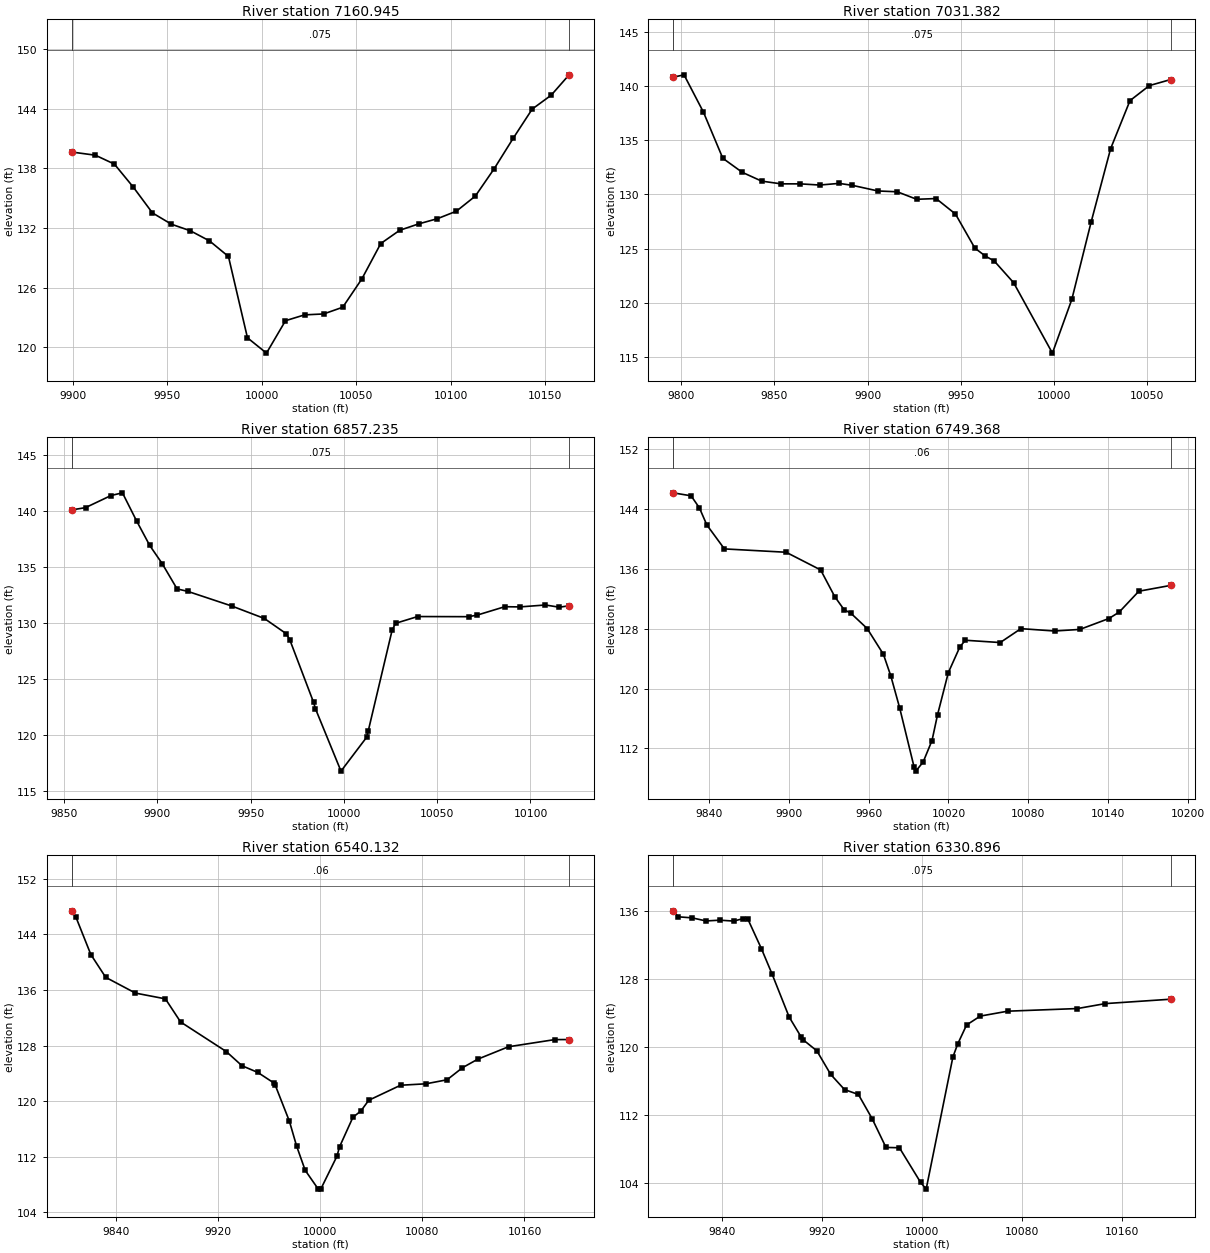
Type RM Length L Ch R = 1 ,7160.945,129.563600,129.563600,129.563600
XS GIS Cut Line= 5
913318.628852038841757.529549952913332.103214498841639.592152194
913337.264291167841604.820374473 913341.01372138841536.937676341
913345.089687204 841495.57584278
#Sta/Elev= 27
9899.375139.65149911.986 139.3289922.051138.43359932.116136.10349942.181133.5208
9952.246132.37979962.311131.71469972.376130.70439982.441129.13099992.506120.9412
10002.57119.397610012.64122.662410022.72123.250310032.83123.342410042.94 124.019
10053.05126.866710063.07130.432610073.08131.7656 10083.1132.409410093.11132.9394
10103.13133.692610113.14135.212410123.17 137.98110133.21141.041410143.26143.9749
10153.31145.372610162.78147.4225
#Mann= 3 , 0 , 0
9899.375   0.075       09899.375   0.075       010162.78   0.075       0
#XS Ineff= 2 , 0
       0                               0
Bank Sta=9899.375,10162.78
Exp/Cntr=0.3,0.1

Type RM Length L Ch R = 1 ,7031.382,174.146800,174.146800,174.146800
XS GIS Cut Line= 2
913367.988683231841780.668489247913442.878971581841524.054217857
#Sta/Elev= 27
9795.488140.82069801.393141.04229811.811 137.6029822.228133.33789832.645132.0429
9843.062131.22979853.479130.97639863.896130.97349874.313130.86569884.731131.0187
9891.905130.83539905.565130.31839915.982130.24239926.399129.54969936.816129.6182
9947.234128.18719957.651125.04219963.294124.30599968.068123.85279978.485121.8446
9999.319115.345610009.74120.301210020.15127.467210030.57134.212610040.99138.6583
10051.41140.048310062.81140.6042
#Mann= 3 , 0 , 0
9795.488   0.075       09795.488   0.075       010062.81   0.075       0
#XS Ineff= 2 , 0
       0                               0
Bank Sta=9795.488,10062.81
Exp/Cntr=0.3,0.1

Type RM Length L Ch R = 1 ,6857.235,107.867200,107.867200,107.867200
XS GIS Cut Line= 2
913406.360693934841830.470516333913588.562857655841635.708587639
#Sta/Elev= 28
9854.001140.08959861.492140.29719875.186141.37839881.284141.61779888.879 139.106
9895.922136.91719902.573135.3046 9910.56133.04449916.267132.82459939.835131.5192
9957.348130.40559969.111129.04139971.042128.47869983.748122.91219984.736122.3514
9998.429116.780510012.12119.789210013.02120.355410025.82129.346110027.66 129.971
10039.51 130.576 10066.9130.563910071.57 130.71210086.21131.453810094.29131.4356
10107.98131.607610115.49131.4096 10120.7131.5384
#Mann= 3 , 0 , 0
9854.001   0.075       09854.001   0.075       0 10120.7   0.075       0
#XS Ineff= 2 , 0
       0                               0
Bank Sta=9854.001,10120.7
Exp/Cntr=0.3,0.1

Type RM Length L Ch R = 1 ,6749.368,209.235800,209.235800,209.235800
XS GIS Cut Line= 6
913474.471960885841956.457267983913511.804416883841897.118074011
913578.790811852841800.442089643913591.946617899841781.735825373
913615.448277572841753.909174677913701.150552796841660.960972912
#Sta/Elev= 30
9813.277146.13889826.813145.74159833.048 144.1379838.628141.85529851.827138.6479
9898.132138.20099924.077135.83839934.644132.2768 9941.62130.53679946.815130.0457
9958.986 128.0129971.157124.57619976.707121.69389983.328117.44339994.251109.4781
9995.499108.9626   10001110.179710007.65113.049410011.79116.483910019.88 122.112
 10028.6125.572110032.69126.444710058.86126.138410074.38127.996210099.61127.6802
10118.64127.893610140.42129.347910148.14130.2036 10162.9132.993910186.72133.7711
#Mann= 3 , 0 , 0
9813.277    0.06       09813.277    0.06       010186.72    0.06       0
#XS Ineff= 2 , 0
       0                               0
Bank Sta=9813.277,10186.72
Exp/Cntr=0.3,0.1

Type RM Length L Ch R = 1 ,6540.132,209.235800,209.235800,209.235800
XS GIS Cut Line= 6
913638.543967515842087.968527802913672.883343091842030.665577952
913703.025784661841984.194323541 913745.35106868841926.226466179
913789.442815872841867.069936467913857.461546173841765.555156604
#Sta/Elev= 30
9805.029147.3962 9808.49146.47759820.148141.10399831.806137.81859855.123135.5492
9878.587134.72099890.506131.39079926.264127.13759938.609125.08829950.991124.1267
9963.373122.63589964.489122.37449975.755117.10629981.447113.50869988.137110.0322
9998.405107.320610000.59 107.40910013.07112.073910015.04113.397810025.53117.6564
10031.81118.579610037.98120.1183 10062.9122.280610082.77122.486510099.35123.0675
10111.39124.802810123.42126.0358 10147.5127.823410183.61 128.84910194.98 128.863
#Mann= 3 , 0 , 0
9805.029    0.06       09805.029    0.06       010194.98    0.06       0
#XS Ineff= 2 , 0
       0                               0
Bank Sta=9805.029,10194.98
Exp/Cntr=0.3,0.1

Type RM Length L Ch R = 1 ,6330.896,209.235800,209.235800,209.235800
XS GIS Cut Line= 6
913850.740862772 842188.82686099913923.253227952842037.542144159
913934.448417629842009.251867851913942.168587665841987.830195582
913960.383648942841947.297520967914019.560491044841828.207362655
#Sta/Elev= 30
 9800.81136.01439805.054135.30829816.143135.18569827.233134.82199838.322134.9146
9849.411 134.8069856.936135.10139860.501135.1096 9871.59131.55419880.072 128.586
9893.769123.51939903.208121.20879904.858120.84579915.947119.53549927.037116.7608
9938.126114.97069949.216114.39749960.305111.52369971.309108.16239982.064108.1229
    9999104.052710003.49103.253210024.88118.801510028.68120.318510035.84122.5762
 10046.8123.622410068.78124.200610124.61124.511110146.94 125.09310199.19125.6098
#Mann= 3 , 0 , 0
 9800.81   0.075       0 9800.81   0.075       010199.19   0.075       0
#XS Ineff= 2 , 0
       0                               0
Bank Sta=9800.81,10199.19
Exp/Cntr=0.3,0.1

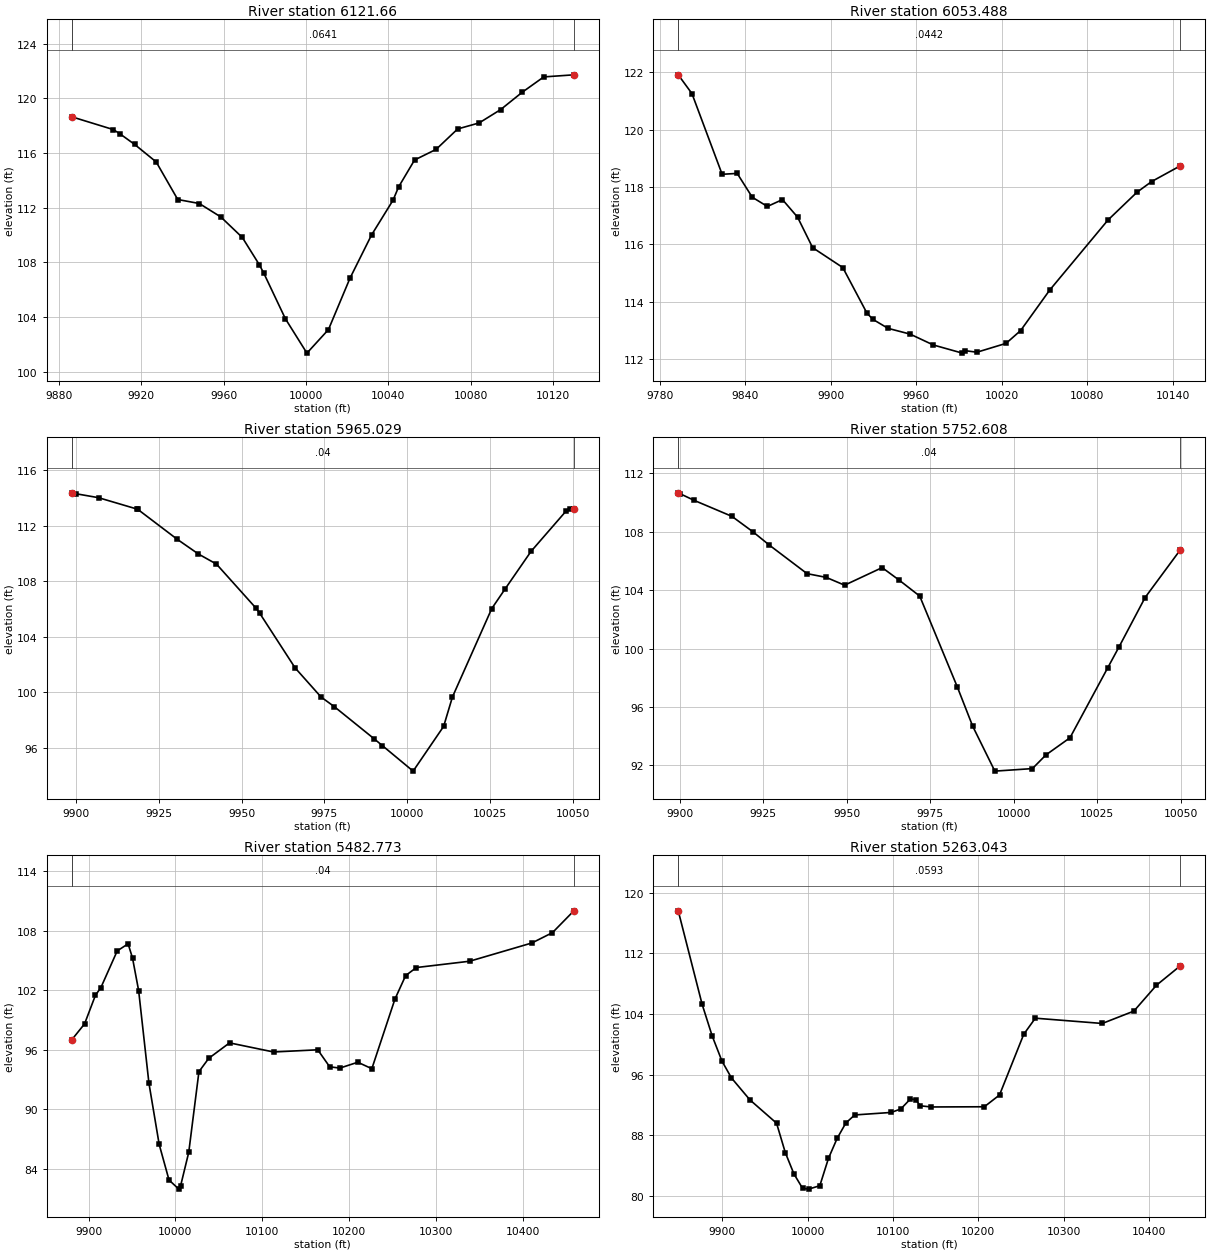
Type RM Length L Ch R = 1 , 6121.66,68.172400,68.172400,68.172400
XS GIS Cut Line= 2
914088.105895979842204.218748657914160.142309309841971.025920442
#Sta/Elev= 26
9886.162118.63959906.276117.70979909.519117.40189916.743116.61859927.209115.3376
9937.675112.59119948.141112.29899958.608111.31619969.074109.81419977.281107.8337
 9979.54107.19279990.007103.868510000.47101.354410010.94103.077310021.41106.8358
10031.87109.992610042.34112.542710045.04113.5098 10052.8115.480510063.27116.2576
10073.74117.7501 10084.2 118.19310094.67119.170310105.14120.4366 10115.6121.5579
10130.23121.7108
#Mann= 3 , 0 , 0
9886.162  0.0641       09886.162  0.0641       010130.23  0.0641       0
#XS Ineff= 2 , 0
       0 9954.93        10039.01       0
Bank Sta=9886.162,10130.23
Exp/Cntr=0.3,0.1

Type RM Length L Ch R = 1 ,6053.488,88.458700,88.458700,88.458700
XS GIS Cut Line= 3
914121.224547734842314.093880195914180.098204439842145.797899181
914216.562195991841975.313182361
#Sta/Elev= 25
9792.761121.91379802.395 121.2599823.584 118.4449834.178118.47439844.772117.6425
9855.366117.32189865.961 117.5619876.555  116.959887.149115.88479908.337115.1897
9925.333113.59749929.526113.3815 9940.12113.06919955.618112.86859971.873  112.49
9992.326112.20489994.494112.289310002.55112.2366   10023112.545110033.23112.9916
10053.68114.404710094.59116.847610115.04 117.82110125.27118.1908 10145.4118.7391
#Mann= 3 , 0 , 0
9792.761  0.0442       09792.761  0.0442       0 10145.4  0.0442       0
#XS Ineff= 2 , 0
       0 9956.48        10030.17       0
Bank Sta=9792.761,10145.4
Exp/Cntr=0.3,0.1

Type RM Length L Ch R = 1 ,5965.029,212.421500,212.421500,212.421500
XS GIS Cut Line= 2
914204.333653777842251.797552814914286.244309084842124.123271934
#Sta/Elev= 24
9898.701114.38799899.935114.32349906.777114.03759918.454113.21329918.658113.1923
9930.539111.03789936.973109.9707 9942.42109.24289954.301106.07919955.492105.6922
9966.182101.74939974.01199.650359978.06398.944999989.944 96.6537 9992.5396.14302
10001.83 94.299410011.0597.5298510013.7199.6518610025.59106.033510029.57107.4322
10037.47110.165210048.09113.085910049.35113.215210050.39113.2482
#Mann= 3 , 0 , 0
9898.701    0.04       09898.701    0.04       010050.39    0.04       0
#XS Ineff= 2 , 0
       0                               0
Bank Sta=9898.701,10050.39
Exp/Cntr=0.3,0.1

Type RM Length L Ch R = 1 ,5752.608,269.834900,269.834900,269.834900
XS GIS Cut Line= 2
914344.800266998842419.289485021914413.341807517842285.621821807
#Sta/Elev= 22
9899.596110.65619900.034110.60729904.417110.13419915.655109.0467 9921.95107.9882
9926.893107.07179938.131105.12669943.866104.86999949.369104.33579960.607105.5378
9965.782104.66659971.845103.58969983.08397.378359987.69994.683379994.32191.61159
10005.56 91.785210009.6192.72136 10016.893.8936310028.0498.6600410031.53 100.136
10039.27103.488710049.81106.7546
#Mann= 3 , 0 , 0
9899.596    0.04       09899.596    0.04       010049.81    0.04       0
#XS Ineff= 2 , 0
       0                               0
Bank Sta=9899.596,10049.81
Exp/Cntr=0.3,0.1

Type RM Length L Ch R = 1 ,5482.773,219.730100,219.730100,219.730100
XS GIS Cut Line= 6
914503.241954177842525.199228488914559.055759682842483.038838713
914658.316186293842423.832634347914799.676888482842312.623514685
914857.665561776842270.514749801914976.129955146842194.323499997
#Sta/Elev= 30
9880.63497.022139895.36998.625999907.902101.51059914.146102.27869932.966105.9773
9945.499106.69079950.582105.25139957.623101.97599969.46992.647239981.26486.48326
9992.61282.8889810003.9481.9769610005.9982.3322410015.3185.6873310027.03 93.8103
10038.3895.1585210062.2996.7113410112.9395.7932510163.8296.0126910177.58    94.3
10189.2794.1706810209.9294.75964 10226.194.1085610252.69101.120110265.05103.4933
10277.41104.300510338.68104.935810410.36106.774910434.03107.814910458.66110.0135
#Mann= 3 , 0 , 0
9880.634    0.04       09880.634    0.04       010458.66    0.04       0
#XS Ineff= 2 , 0
       0                10066.33       0
Bank Sta=9880.634,10458.66
Exp/Cntr=0.3,0.1

Type RM Length L Ch R = 1 ,5263.043,219.730200,219.730200,219.730200
XS GIS Cut Line= 6
914719.913097253842707.314997615914757.619136801842646.521224559
914789.818740695842504.285135004 914839.05844427842413.622240935
914923.264898882842326.031851504915039.719977238842239.566660389
#Sta/Elev= 30
9848.246117.62219876.214105.30249888.027101.11969899.49597.80146 9910.6295.58078
9932.26492.686849963.47389.613589973.70685.740089983.81482.931149993.92281.02884
   1000180.9161810014.1881.3666710024.3384.9836810034.4787.60981 10044.789.64127
 10055.190.7004510097.8391.0306910109.1391.4929410120.4392.8192510126.48 92.7042
10131.9891.9062710144.65 91.752710206.9891.7794310224.7693.3312110253.18101.3429
10266.75103.461410345.18102.765810382.26104.398410408.72107.808710436.66110.3697
#Mann= 3 , 0 , 0
9848.246  0.0593       09848.246  0.0593       010436.66  0.0593       0
#XS Ineff= 2 , 0
       0                   10113       0
Bank Sta=9848.246,10436.66
Exp/Cntr=0.3,0.1