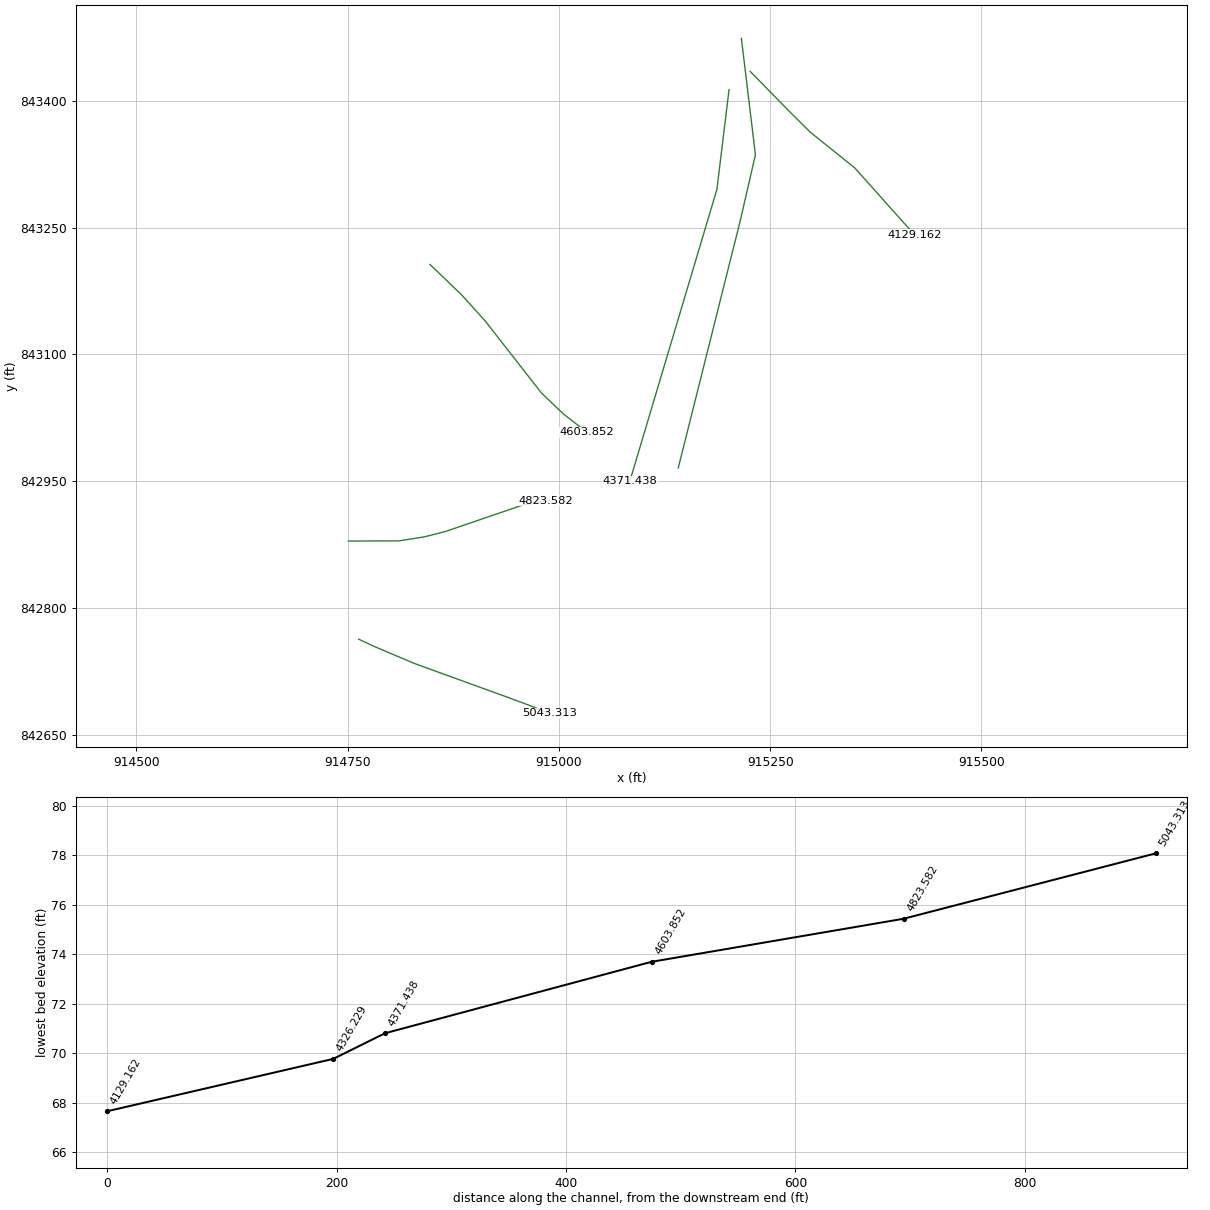
HEC-RAS study 16792_ras.prj: 16792

--- 16792_ras.g01 (geometry) --- (continued)

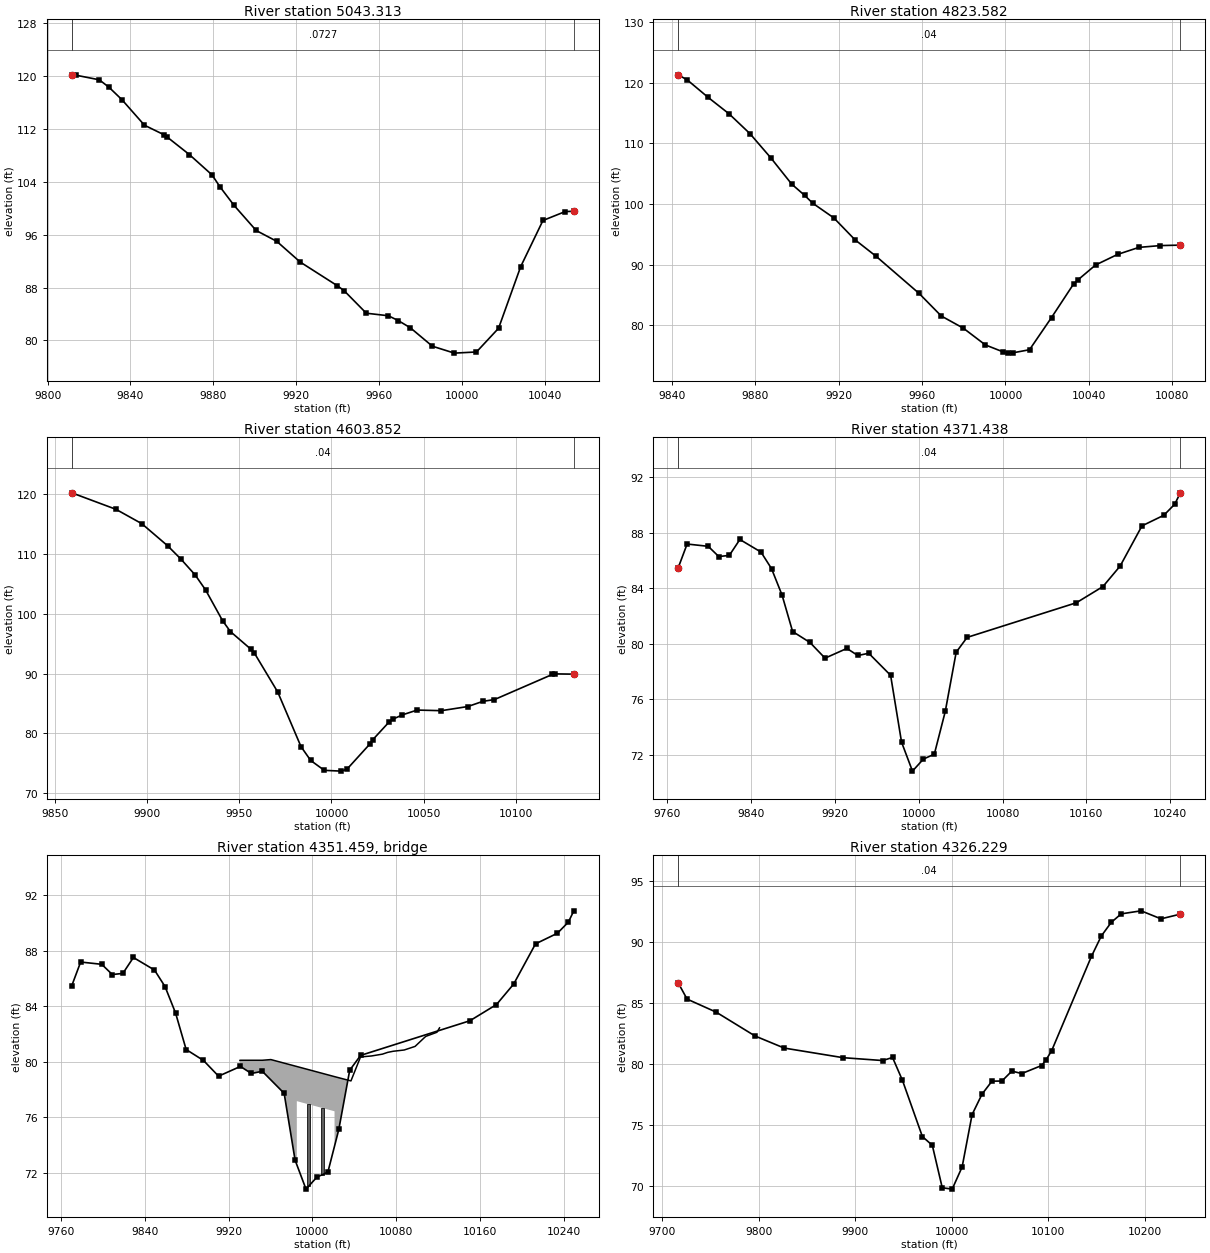
Type RM Length L Ch R = 1 ,5043.313,219.730200,219.730200,219.730200
XS GIS Cut Line= 6
914762.989906139  842762.9800171914779.292622924 842755.25891018
914828.688334333 842734.30305333914939.261595203842694.198111478
914964.828008736 842684.69378207914988.872544891842675.159670676
#Sta/Elev= 29
9811.683 120.1959813.907120.12579824.972119.44249829.721118.29459835.921116.4277
9846.784112.56779855.989111.15779857.646110.80279868.509 108.1159879.372105.0594
9883.378103.19059890.092100.4177 9900.7396.632639910.66494.992849922.00591.85324
9939.99388.256129943.27987.494179953.91784.109759964.55483.726969969.32282.99823
9975.19281.903859985.82979.113069996.46678.0681410007.1278.2452310017.79 81.8333
10028.4691.1535410039.2298.1474210049.9899.4971710054.1499.53689
#Mann= 3 , 0 , 0
9811.683  0.0727       09811.683  0.0727       010054.14  0.0727       0
#XS Ineff= 2 , 0
       0                               0
Bank Sta=9811.683,10054.14
Exp/Cntr=0.3,0.1

Type RM Length L Ch R = 1 ,4823.582,219.730200,219.730200,219.730200
XS GIS Cut Line= 6
914750.657572664842879.098746695914811.155824958842879.343183683
914840.998185905842884.151578415914864.941923669842890.193159565
914956.100764012842921.374654362914984.510831487842926.875191357
#Sta/Elev= 28
9843.045121.2852 9847.41120.4362 9857.42117.55769867.429114.85699877.441111.5939
9887.456107.60079897.471103.27429903.636101.4348 9907.53100.13429917.65997.71208
9927.78894.11681 9937.9991.372889958.55785.269219969.19681.549669979.773 79.5425
 9990.3576.78116    999975.6142410000.9875.4276310003.6975.4868110011.5375.98789
10022.0881.2905310032.6486.8061510034.9787.5565310043.1989.9432110053.7491.68969
   1006492.8523810074.2193.1466310083.8693.22571
#Mann= 3 , 0 , 0
9843.045    0.04       09843.045    0.04       010083.86    0.04       0
#XS Ineff= 2 , 0
       0                               0
Bank Sta=9843.045,10083.86
Exp/Cntr=0.3,0.1

Type RM Length L Ch R = 1 ,4603.852,232.414300,232.414300,232.414300
XS GIS Cut Line= 6
914847.471087617843206.394104937914884.790099595843170.478266954
914912.560279822843139.798027077914979.138603964843054.515818524
915005.289836618843029.476333895915033.071107668843007.950716825
#Sta/Elev= 30
9858.892120.25199882.905117.49369896.949115.08789911.011111.38199918.088109.1993
9925.913106.51939931.576104.01589940.81498.866299945.06497.045349956.06394.12559
9958.15193.418669970.80286.920289983.45477.778179988.71275.470719996.10573.81888
 10005.473.6885810008.4974.0375910020.8978.23736 10022.378.9008910031.4481.95521
10033.4182.3864710038.5283.1016810046.5583.9049810059.6883.8028110074.0884.49526
10082.28 85.367210088.5485.6595310119.9289.8560210121.6289.9596710131.6889.91345
#Mann= 3 , 0 , 0
9858.892    0.04       09858.892    0.04       010131.68    0.04       0
#XS Ineff= 2 , 0
       0                 10048.3       0
Bank Sta=9858.892,10131.68
Exp/Cntr=0.3,0.1

Type RM Length L Ch R = 1 ,4371.438,45.209100,45.209100,45.209100
XS GIS Cut Line= 3
915201.318004402843413.412454792915186.963768986843295.384608303
915083.878665948842949.925136093
#Sta/Elev= 30
9770.26585.477749778.73987.187759798.88687.02261 9808.9686.285779819.03486.36537
9829.10787.514889849.25586.608899859.32885.415139869.40283.502329879.47680.87535
 9896.0380.085749910.43578.952879931.30679.655419941.74279.145719952.17879.30556
9973.04977.715119983.48572.897729993.92170.8026510004.3671.6723910014.7972.02598
10025.2375.1055510035.6679.38124 10046.180.4518810150.4682.9518710175.8184.12062
 10192.285.5969410213.0788.4977510233.9489.2631110244.3890.0631710249.6790.88174
#Mann= 3 , 0 , 0
9770.265    0.04       09770.265    0.04       010249.67    0.04       0
#XS Ineff= 2 , 0
       09966.796        10040.53       0
Bank Sta=9770.265,10249.67
Exp/Cntr=0.3,0.1

Type RM Length L Ch R = 3 ,4351.459,,,
BEGIN DESCRIPTION:
END DESCRIPTION:
Bridge Culvert--1,0,-1,-1, 0
Deck Dist Width WeirC Skew NumUp NumDn MinLoCord MaxHiCord MaxSubmerge Is_Ogee
7.104550,31.000000,2.6,0, 21, 21, , , 0.95, 0, 0,0,,
 9930.82 9931.34 9941.76 9952.19 9960.38 9985.16 9985.1610021.1610021.1610036.84
10045.9810056.4010066.8210071.9410077.2410087.6610098.0810107.4710108.5110118.93
10121.43
   80.09   80.10   80.10   80.10   80.15   79.65   79.65   78.92   78.92   78.61
   80.34   80.41   80.54   80.67   80.75   80.84   81.10   81.77   81.83   82.12
   82.44
 -919.91 -919.90 -919.90 -919.90 -919.85 -920.35   77.15   76.42 -921.08 -921.39
 -919.66 -919.59 -919.46 -919.33 -919.25 -919.16 -918.90 -918.23 -918.17 -917.88
 -917.56
 9930.82 9931.34 9941.76 9952.19 9960.38 9982.53 9982.5310018.5310018.5310036.84
10045.9810056.4010066.8210071.9410077.2410087.6610098.0810107.4710108.5110118.93
10121.43
   80.09   80.10   80.10   80.10   80.15   79.70   79.70   78.98   78.98   78.61
   80.34   80.41   80.54   80.67   80.75   80.84   81.10   81.77   81.83   82.12
   82.44
 -919.91 -919.90 -919.90 -919.90 -919.85 -920.30   77.20   76.48 -921.02 -921.39
 -919.66 -919.59 -919.46 -919.33 -919.25 -919.16 -918.90 -918.23 -918.17 -917.88
 -917.56
Pier Skew, UpSta & Num, DnSta & Num=  ,9996.66, 2 ,9994.03, 2 , 0 , 0 , 0 ,,
    3.00    3.00
 -920.58   79.42
    3.00    3.00
 -920.53   79.47
Pier Skew, UpSta & Num, DnSta & Num=  ,10009.66, 2 ,10007.03, 2 , 0 , 0 , 0 ,,
    3.00    3.00
 -920.85   79.15
    3.00    3.00
 -920.79   79.21
BR Coef=-1 , 0 , 0 ,, 0 ,,,0.8,0,1,0,
WSPro=,,,, 1 ,,,, 0 ,,,, 0 ,,,,-1 ,-1 ,-1 , 0 , 0 , 0 , 0 , 0
BC Design=,, 0 ,, 0 ,,,,,,

Type RM Length L Ch R = 1 ,4326.229,197.066900,197.066900,197.066900
XS GIS Cut Line= 4
915215.906128495843474.094990755915232.532127714843336.278125105
915214.310315886843257.147904305915141.170332614842965.550136093
#Sta/Elev= 30
9716.42786.648779725.58885.325849755.80584.255599796.09582.303599826.31381.31541
 9887.3480.527979928.38680.294139938.65880.545729948.96878.665389969.58874.07344
9979.89873.352199990.20769.8785410000.5269.7658810010.8371.5834310021.1475.86731
10031.4577.5435210041.76 78.606410052.0778.6150410062.3879.4289510072.6979.22854
10093.3179.8876110098.0280.3727710103.6181.0911510144.8588.8136210155.1690.49271
10165.4791.6080110175.7892.30307 10196.492.5518210217.0291.8956510237.0792.27995
#Mann= 3 , 0 , 0
9716.427    0.04       09716.427    0.04       010237.07    0.04       0
#XS Ineff= 2 , 0
       09961.442        10040.33       0
Bank Sta=9716.427,10237.07
Exp/Cntr=0.3,0.1

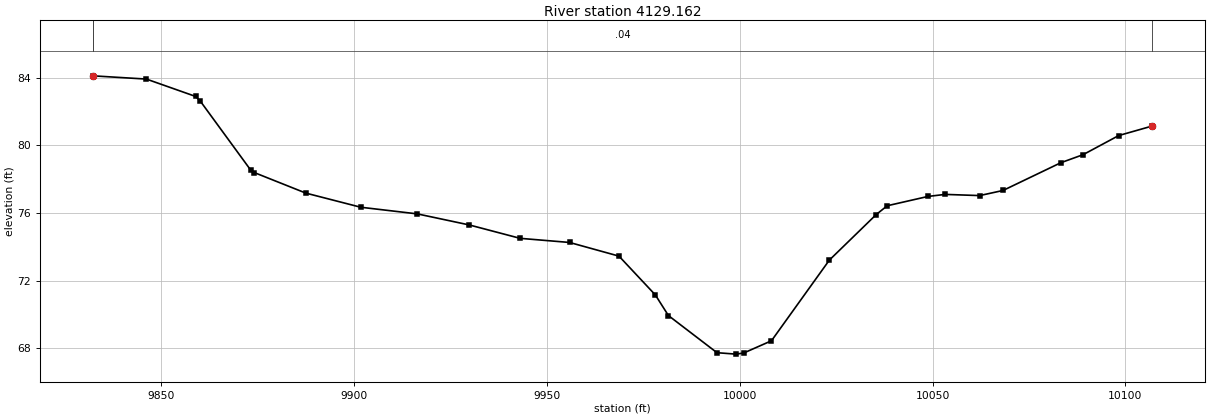
Type RM Length L Ch R = 1 ,4129.162,0.000000,0.000000,0.000000
XS GIS Cut Line= 6
915226.340121328843434.944192069915271.861140532 843388.43378455
 915297.75528104 843362.76692687915348.654010738843321.926923988
915350.190222354843320.646278089915420.817595261843241.580057356
#Sta/Elev= 30
9832.20384.110819846.11783.91814 9858.88 82.8909 9860.1182.608779873.17778.53026
9874.10278.387749887.47477.173179901.70276.338189916.36575.945459929.86375.29012
9943.03174.499089955.85274.255369968.67373.446499978.11171.149369981.49469.93179
 9994.0967.73515    999967.65057   1000167.7149810008.2268.4408410023.2373.21107
10035.3975.9070810038.2476.42638 10048.876.9765310053.2577.0975810062.2177.02793
10068.2677.3293310083.2778.9720610089.02 79.445410098.2880.5787310107.0281.14544
#Mann= 3 , 0 , 0
9832.203    0.04       09832.203    0.04       010107.02    0.04       0
#XS Ineff= 2 , 0
       0                               0
Bank Sta=9832.203,10107.02
Exp/Cntr=0.3,0.1